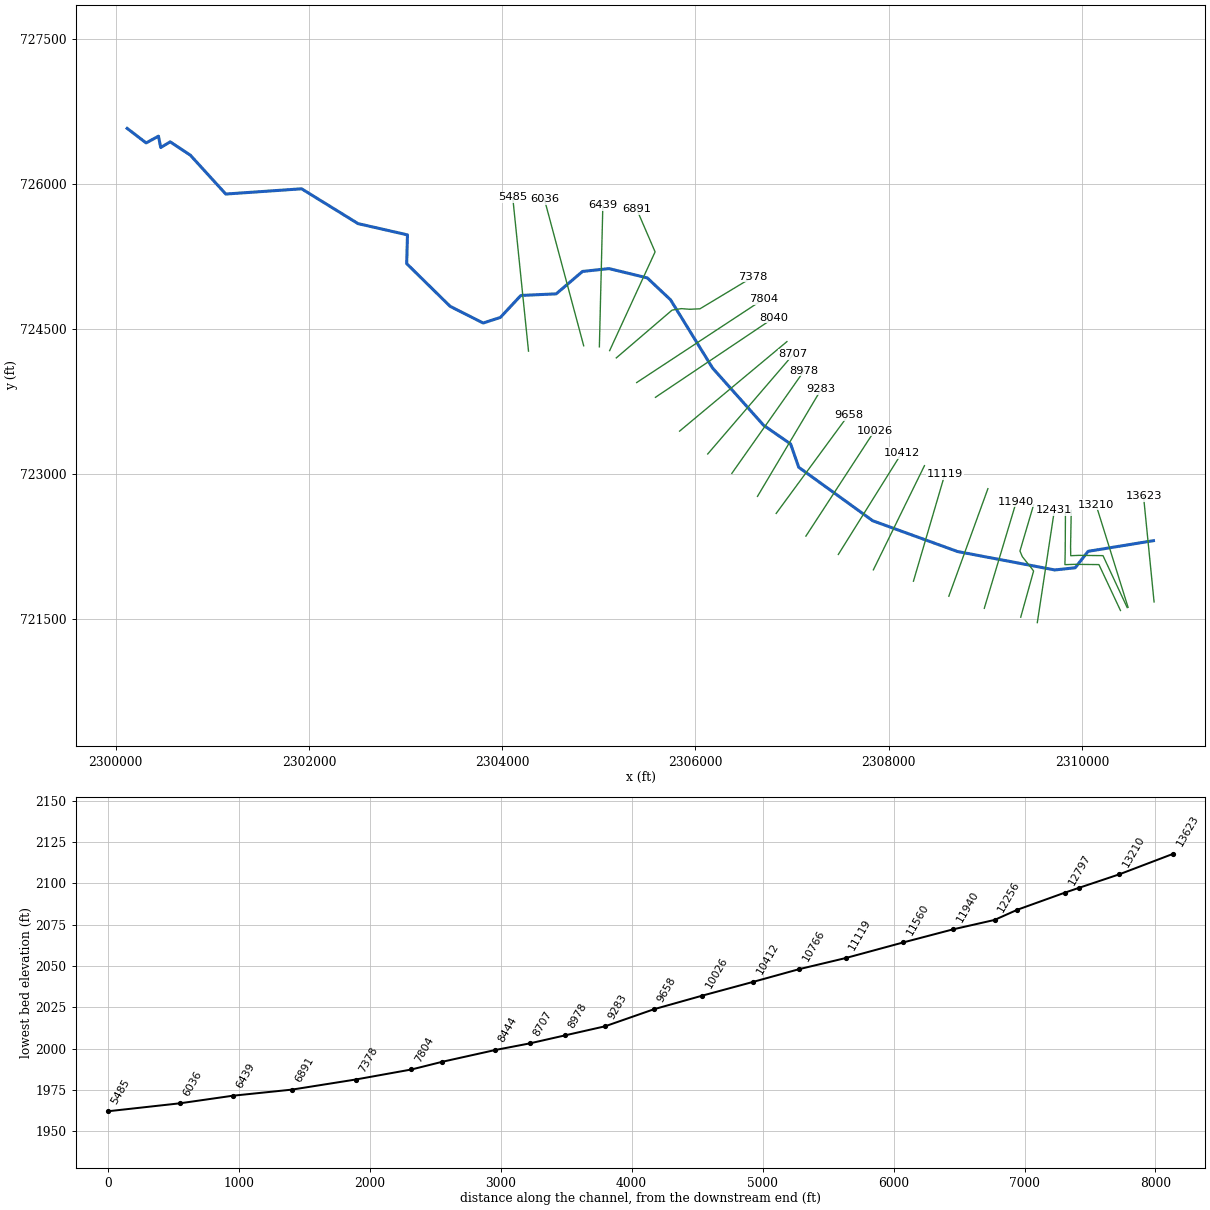
--- STALNAKRN2.prj (project) ---

Proj Title=STALNAKRN2
Current Plan=p01
Default Exp/Contr=0,0
English Units
Geom File=g01
Flow File=f01
Plan File=p01
BEGIN DESCRIPTION:
----------MODEL BY WOOD PLC 2022----------
AFH study
Randolph County, WV
HEC-RAS Version: RAS 6.2
Vertical Datum: NAVD88
Projection: NAD 1983 StatePlane West Virginia S FIPS 4702 (US Feet)
Terrain: 1-meter LIDAR (FEMA Region III 3DEP collected 2016-2018)
Land Use: 2019 NLCD
Hydrologic Method:
WV SIR2010-5033 regression equations
Additional Model Notes:
None
END DESCRIPTION:
DSS File=dss
DSS Export Rating Curves= 0
DSS Export Rating Curve Sorted= 0
DSS Export Volume Flow Curves= 0
DXF OffsetX= 0
DXF OffsetY= 0
DXF ScaleX= 0
DXF ScaleY= 0

--- STALNAKRN2.p01 (plan) ---

Plan Title=Floodplain
Program Version=6.20
Short Identifier=Floodplain
Geom File=g01
Flow File=f01
Subcritical Flow
K Sum by GR= 0
Std Step Tol= 0.01
Critical Tol= 0.01
Num of Std Step Trials= 20
Max Error Tol= 0.3
Flow Tol Ratio= 0.001
Split Flow NTrial= 30
Split Flow Tol= 0.02
Split Flow Ratio= 0.02
Log Output Level= 0
Friction Slope Method= 1
Unsteady Friction Slope Method= 2
Unsteady Bridges Friction Slope Method= 1
Parabolic Critical Depth
Global Vel Dist= 0 , 0 , 0
Global Log Level= 0
CheckData=True
Encroach Param=-1 ,0,0, 0
Computation Interval=0.1SEC
Output Interval=1SEC
Instantaneous Interval=Max Profile
Mapping Interval=1HOUR
Computation Time Step Use Courant=        0
Computation Time Step Use Time Series=    0
Computation Time Step Count To Double=0
Computation Time Step Max Doubling=0
Computation Time Step Max Halving=0
Computation Time Step Residence Courant=0
Run HTab= 0
Run UNet= 0
Run Sediment= 0
Run PostProcess= 0
Run WQNet= 0
Run RASMapper=-1
UNET Theta= 0
UNET Theta Warmup= 0
UNET ZTol= 0
UNET ZSATol= 0
UNET MxIter= 0
UNET Max Iter WO Improvement= 0
UNET MaxInSteps= 0
UNET DtIC= 0
UNET DtMin= 0
UNET MaxCRTS= 0
UNET WFStab= 0
UNET SFStab= 0
UNET WFX= 1
UNET SFX= 1
UNET Gravity=32.174
UNET 1D Methodology=Finite Difference
UNET DSS MLevel= 1
UNET Pardiso=0
UNET DZMax Abort= 0
UNET Use Existing IB Tables= 0
UNET Froude Reduction=False
UNET Froude Limit= 0
UNET Froude Power= 0
UNET D1 Cores= 0
UNET WindReference=Eulerian
UNET WindDragFormulation=Hsu (1988)
UNET D2 Coriolis=0
UNET D2 Cores= 0
UNET D2 Theta= 1
UNET D2 Theta Warmup= 1
UNET D2 Z Tol= 0.01
UNET D2 Volume Tol= 0.01
UNET D2 Max Iterations= 20
UNET D2 Equation= 0
UNET D2 RampUpFraction=0.1
UNET D2 TimeSlices= 1
UNET D2 Turbulence Formulation=Non-Conservative (original)
UNET D2 Eddy Viscosity=0.3
UNET D2 Transverse Eddy Viscosity=0.1
UNET D2 Smagorinsky Mixing=0
UNET D2 BCVolumeCheck=0
UNET D2 Cores=0
UNET D2 SolverType=PARDISO (Direct)
UNET D2 Minimum Iterations= 2147483647
UNET D2 Maximum Iterations= 2147483647
UNET D2 Restart Number= 10
UNET D2 Relaxation Coeff=1.3
UNET D2 SOR Precondition Iterations= 10
UNET D2 ILUT Maximum Fill= 8
UNET D2 ILUT Tolerance=1E-08
UNET D1D2 MaxIter= 0
UNET D1D2 ZTol=0.01
UNET D1D2 QTol=0.1
UNET D1D2 MinQTol=1
DSS File=dss
Write IC File= 0
Write IC File at Fixed DateTime=0
Write IC File at Sim End=0
Echo Input=False
Echo Parameters=False
Echo Output=False
Write Detailed= 0
HDF Write Warmup=0
HDF Write Time Slices=0
HDF Flush=0
HDF Compression= 1
HDF Chunk Size= 1
HDF Spatial Parts= 1
HDF Use Max Rows=0
HDF Fixed Rows= 1
Calibration Method= 0
Calibration Iterations= 20
Calibration Max Change=0.05
Calibration Tolerance=0.2
Calibration Maximum=1.5
Calibration Minimum=0.5
Calibration Optimization Method= 1
WQ AD Non Conservative
WQ ULTIMATE=-1
WQ Max Comp Step=1HOUR
WQ Output Interval=15MIN
WQ Output Selected Increments= 0
WQ Output face flow=0
WQ Output face velocity=0
WQ Output face area=0
WQ Output face dispersion=0
WQ Output cell volume=0
WQ Output cell surface area=0
WQ Output cell continuity=0
WQ Output cumulative cell continuity=0
WQ Output face conc=0
WQ Output face dconc_dx=0
WQ Output face courant=0
WQ Output face peclet=0
WQ Output face adv mass=0
WQ Output face disp mass=0
WQ Output cell mass=0
WQ Output cell source sink temp=0
WQ Output nsm pathways=0
WQ Output nsm derived pathways=0
WQ Create Restart=0
WQ Fixed Restart=0
WQ System Summary=0
WQ Write To DSS=0
Sorting and Armoring Iterations= 10
XS Update Threshold= 0.02
Bed Roughness Predictor= 0
Hydraulics Update Threshold= 0.02
Energy Slope Method= 1
Volume Change Method= 1
Sediment Retention Method= 0
Sediment TS Multiplier= 1
Warm Up Method= 0
XS Weighting Method= 0
Number of US Weighted Cross Sections= 1
Number of DS Weighted Cross Sections= 1
Upstream XS Weight=0
Main XS Weight=1
Downstream XS Weight=0
Number of DS XS's Weighted with US Boundary= 1
Upstream Boundary Weight= 1
Weight of XSs Associated with US Boundary= 0
Number of US XS's Weighted with DS Boundary= 1
Downstream Boundary Weight= 0.5
Weight of XSs Associated with DS Boundary= 0.5
Percentile Method= 0
Sediment Output Level= 3
Mass or Volume Output= 0
Output Increment Type= 1
Profile and TS Output Increment= 1
Transport Output Increment 1
XS Output Flag= 0
XS Output Increment= 10
Read HDF5 Sediment Hotstart= 0
Sediment Hotstart Type= 0
Write Gradation File= 0
Read Gradation Hotstart= 0
Write HDF5 File= 1
Write Binary Output= 1
Write DSS Sediment File= 0
DSS Sediment Output Type= 1
SV Curve= 0
Specific Gage Flag= 0
Subcell Erosion Methods= 0
Subcell Deposition Methods= 0
Advection Scheme= 1
Matrix Solver= 0
Implicit Weighting Factor= 1
Maximum Outer Loop Convergence Iterations= 5
Convergence Maximum Absolute= 0.001
Convergence RMSE= 0.0001
Grain Fractions Max Abs Error= 0.001
Max Subgrid Regions= 1
Max Subgrid Length Scale= 3.402823E+38
Initial Layer Thickness= 3.402823E+38
Min Layer Thickness= 3.402823E+38
Max Layer Thickness= 3.402823E+38
Number of Layers= 5

--- STALNAKRN2.f01 (steady flow) ---

Flow Title=Flow
Program Version=6.20
Number of Profiles= 1
Profile Names=P100yr
River Rch & RM=STALNAKRN2,Main,13623
     481
River Rch & RM=STALNAKRN2,Main,10026
     550
River Rch & RM=STALNAKRN2,Main,7378
    1210
Boundary for River Rch & Prof#=STALNAKRN2,Main            , 1
Up Type= 0
Dn Type= 3
Dn Slope=0.00541
DSS Import GetInterval= 0
DSS Import GetPeak= 0
DSS Import FillOption= 0

--- STALNAKRN2.g01 (geometry) ---

Geom Title=Geometry
Program Version=6.20

River Reach=STALNAKRN2      ,Main
Reach XY= 30
     2310740.171      722312.525     2310064.172      722202.282
     2309930.839       722032.36     2309719.728      722009.444
     2308712.452      722200.209     2307835.108      722518.655
     2307069.374       723071.91     2306985.348      723313.067
     2306704.693      723507.389     2306176.976      724099.941
      2305742.48      724805.134     2305501.904      725031.541
     2305105.745      725127.827     2304831.534      725098.172
     2304559.407      724866.466     2304193.616      724849.888
     2303981.454      724622.155     2303803.316      724564.724
     2303461.696      724737.328      2303012.17      725179.133
     2303020.185      725476.727     2302508.784      725593.109
     2301924.731      725953.539     2301139.781      725899.226
     2300772.638      726301.962     2300564.279      726439.316
     2300466.562      726380.609     2300443.274       726497.97
     2300315.779      726428.092     2300119.069      726578.694

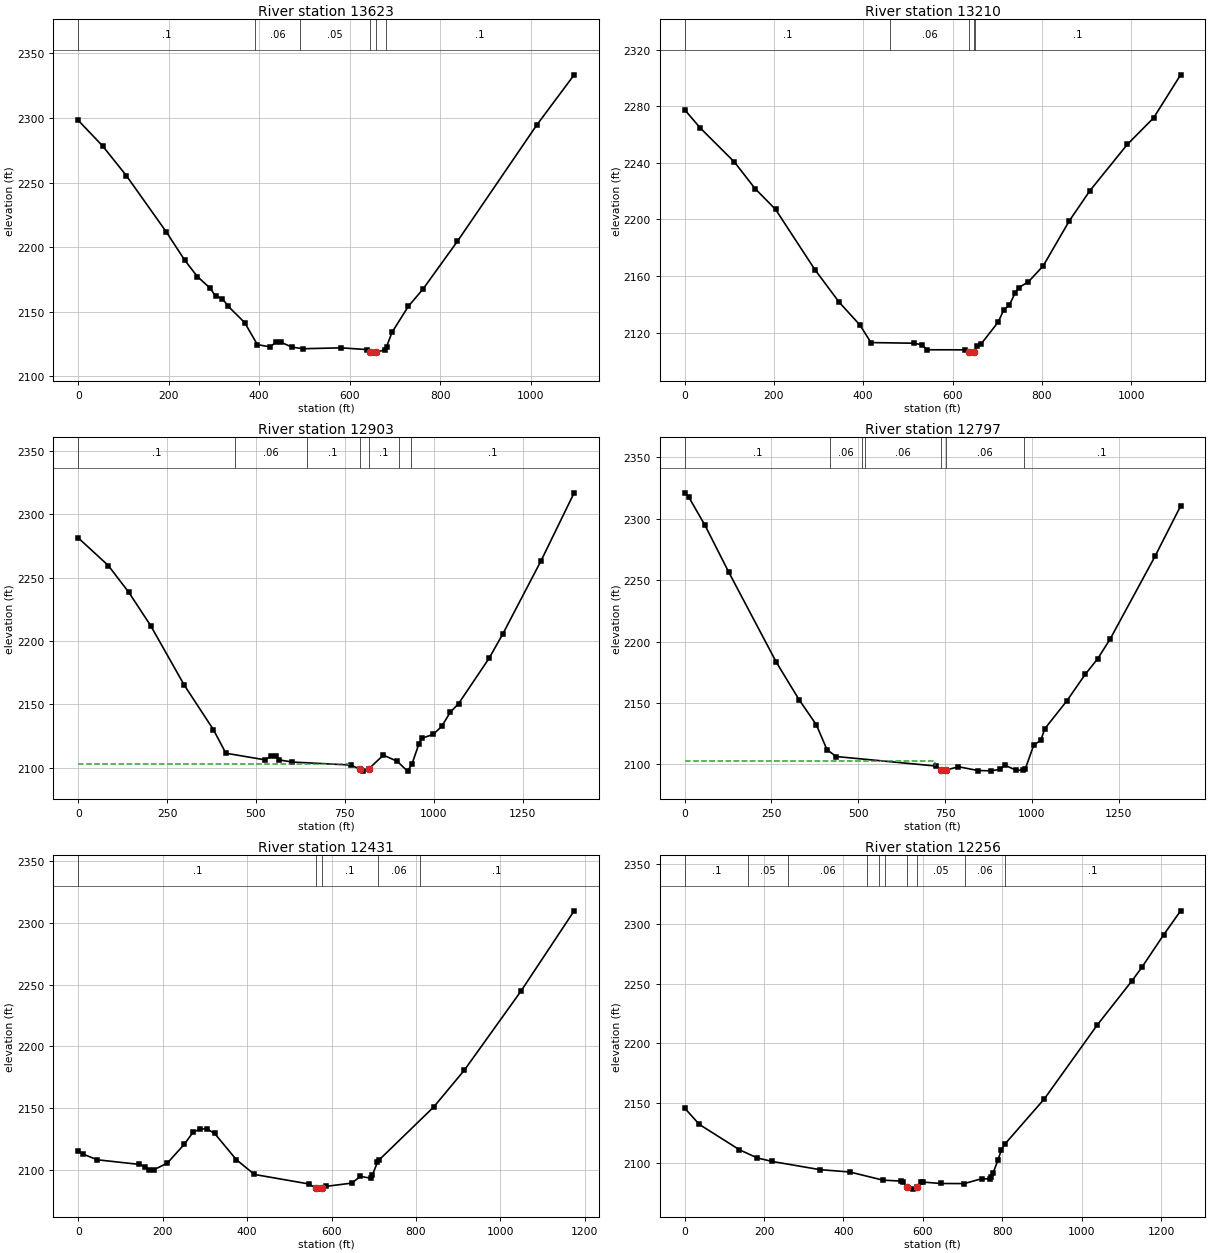
Type RM Length L Ch R = 1 ,13623   ,412.7,412.7,412.7
XS GIS Cut Line= 2
2310746.67928394721679.1791878452310637.84616232722769.777760795
#Sta/Elev= 30
       0 2298.24    54.3 2278.23   106.5 2255.36     195 2211.68   235.2 2190.06
   263.3 2177.33   291.4 2168.33   303.5 2162.25   318.5 2160.31   331.6 2154.24
   367.8 2141.69     396 2124.63   424.1 2122.84   436.2 2126.29   448.2 2126.42
   472.3 2122.71   496.5 2121.44   580.9 2122.13   637.1 2120.81   644.62118.767
   653.2 2118.04   658.4 2118.78   677.3 2120.56   681.4 2122.96   693.4 2134.09
   729.6 2154.26   761.8 2167.54   838.1 2204.62  1012.9 2294.35    1096 2333.44
#Mann= 6 ,-1,0
       0      .1       0     390     .06       0     490     .05       0
   644.6    .045       0   658.4     .05       0     680      .1       0
Bank Sta=644.6,658.4
XS Rating Curve= 0 ,0
Exp/Cntr(USF)=0,0
Exp/Cntr=0.3,0.1

Type RM Length L Ch R = 1 ,13210   ,306.7,306.7,306.7
BEGIN DESCRIPTION:
Structure XS 4
END DESCRIPTION:
XS GIS Cut Line= 2
2310477.55426978721622.722061813 2310146.4040763722683.217422627
#Sta/Elev= 30
       0 2277.53      35 2264.58   111.6  2240.5   157.6 2221.83   203.7 2207.05
   291.7 2164.56   346.2  2141.5   392.3 2125.52   417.4 2113.02   513.8 2112.57
   530.6 2111.51   543.1 2107.94     627  2107.9  636.732106.318   643.7 2105.57
   648.1 2106.34   654.5 2110.77   664.7 2112.31   702.5 2127.57     715  2136.3
   727.5 2139.51   740.1 2148.05   748.5 2151.92   769.5 2155.78     803 2167.12
   861.6 2198.98   907.7 2220.29   991.5 2252.98  1050.5 2271.76    1111 2302.18
#Mann= 5 ,-1,0
       0      .1       0     460     .06       0  636.73    .045       0
   648.1     .06       0     650      .1       0
Bank Sta=636.73,648.1
XS Rating Curve= 0 ,0
Exp/Cntr(USF)=0,0
Exp/Cntr=0.5,0.3

Type RM Length L Ch R = 1 ,12903   ,106.6,106.6,106.6
BEGIN DESCRIPTION:
Structure XS 3 28.9ft
END DESCRIPTION:
XS GIS Cut Line= 6
2310468.25656677721620.6296335142310218.08838804722157.761199422
2309968.61698261722160.3964607472309884.28427832722157.054215687
2309882.63136987722248.5276714492309889.52682379722625.807558011
#Sta/Elev= 30
       0 2281.24    84.8 2259.39   142.3 2238.31   203.6 2212.16   298.5 2165.13
   380.1 2130.21   415.4 2111.52   525.7  2106.3   543.4 2109.48   556.6 2108.97
   565.4 2106.24   602.4 2104.55   766.5 2102.21  791.552099.069   802.5 2097.67
   816.92099.052   858.5 2110.03   897.5 2105.14   926.4 2097.41   938.7 2102.76
   958.5 2118.95   966.5 2123.29   998.6 2126.36  1022.6 2132.66  1046.6 2143.76
    1070 2150.61  1155.6 2186.22  1194.6 2205.57  1302.3 2263.34  1395.2 2316.74
#Mann= 7 ,-1,0
       0      .1       0     440     .06       0  642.53      .1       0
  791.55    .045       0   816.9      .1       0  902.02     .06       0
  936.42      .1       0
#XS Ineff= 2 , 0
          762.65 2102.93   845.8         2096.03
Permanent Ineff=
       F       F
Bank Sta=791.55,816.9
XS Rating Curve= 0 ,0
Exp/Cntr(USF)=0,0
Exp/Cntr=0.5,0.3

Type RM Length L Ch R = 1 ,12797   ,365.3,365.3,365.3
BEGIN DESCRIPTION:
Structure XS 2 49.7ft 16.57
END DESCRIPTION:
XS GIS Cut Line= 6
2310399.03901317721589.9904619992310176.14197881722065.042165894
2309926.67057338722067.6774272192309824.30195238722064.335182159
2309827.15802311722218.9343464222309829.67839559722616.115429456
#Sta/Elev= 30
       0 2321.07    12.4  2317.3    58.7 2294.53   127.2 2256.35   264.2 2183.07
   329.3 2152.78   379.1  2132.3     410 2111.94   436.5 2106.41   724.7 2098.64
   738.6 2095.34   744.7 2094.53  752.042095.372   788.7 2098.08   844.8 2095.03
   881.5 2094.79   909.5 2095.99   921.5 2099.43   953.5 2095.42   973.5  2095.2
   981.5 2096.63  1005.5  2115.8  1025.5 2119.55  1037.5 2129.12    1101 2151.81
  1153.5 2173.22  1189.5    2186  1225.3 2201.93  1354.6  2269.3  1428.5 2310.35
#Mann= 7 ,-1,0
       0      .1       0     420     .06       0     510      .1       0
     520     .06       0   738.6    .045       0  752.04     .06       0
  976.65      .1       0
#XS Ineff= 2 , 0
          722.03 2102.93  768.61         2096.03
Permanent Ineff=
       F       F
Bank Sta=738.6,752.04
XS Rating Curve= 0 ,0
Exp/Cntr(USF)=0,0
Exp/Cntr=0.3,0.1

Type RM Length L Ch R = 1 ,12431   ,175,175,175
XS GIS Cut Line= 2
2309538.52681619721464.614624111 2309714.7731075722625.766660957
#Sta/Elev= 30
       0 2115.17    12.5 2112.37    45.1 2107.91   144.3 2104.17   158.4 2102.45
     167 2100.01   178.6 2099.73     211 2105.21   250.9 2120.36   271.6 2130.05
   287.8 2132.81     304 2133.08   323.1 2129.25   374.3 2108.06   417.3    2096
   546.4 2088.29     564 2084.67   570.7  2084.1     578 2084.84   587.2 2086.35
   647.9 2088.99   668.1 2094.39   692.4 2093.01   696.5 2095.43   708.6 2105.87
   712.6 2107.78   842.1  2150.8   914.5 2180.64  1048.1 2244.51  1174.5 2309.87
#Mann= 5 ,-1,0
       0      .1       0     564    .045       0     578      .1       0
     710     .06       0     810      .1       0
Bank Sta=564,578
XS Rating Curve= 0 ,0
Exp/Cntr(USF)=0,0
Exp/Cntr=0.3,0.1

Type RM Length L Ch R = 1 ,12256   ,316.7,316.7,316.7
BEGIN DESCRIPTION:
Structure
END DESCRIPTION:
XS GIS Cut Line= 6
2309366.77428126721520.9655506622309499.81817542 721998.19778102
2309481.74368073722023.5020735782309382.93644312722147.613603743
2309358.83711688722205.4519867332309500.79630431722686.212983366
#Sta/Elev= 30
       0 2145.74      37 2132.08   137.7  2110.9   182.9    2104   220.3 2101.08
   340.7  2094.2   415.5 2092.27   499.1 2085.45     544 2084.62   549.1 2084.16
   559.4 2079.39   574.4  2077.9   584.9 2079.35   595.2 2083.59   600.3  2083.8
   645.5 2082.62   704.2 2082.53   747.8 2086.61   768.4 2086.39   772.6 2088.26
   776.7 2091.43   789.2 2102.26   797.6 2110.86   805.9  2115.4     906 2153.53
  1039.5 2215.52  1127.1 2252.57  1151.2 2263.52  1206.3 2290.83  1249.1 2310.96
#Mann= 10 ,-1,0
       0      .1       0     160     .05       0     260     .06       0
     460     .05       0     490      .1       0  505.43     .05       0
   559.4    .045       0   584.9     .05       0  705.17     .06       0
  807.82      .1       0
Bank Sta=559.4,584.9
XS Rating Curve= 0 ,0
Exp/Cntr(USF)=0,0
Exp/Cntr=0.3,0.1

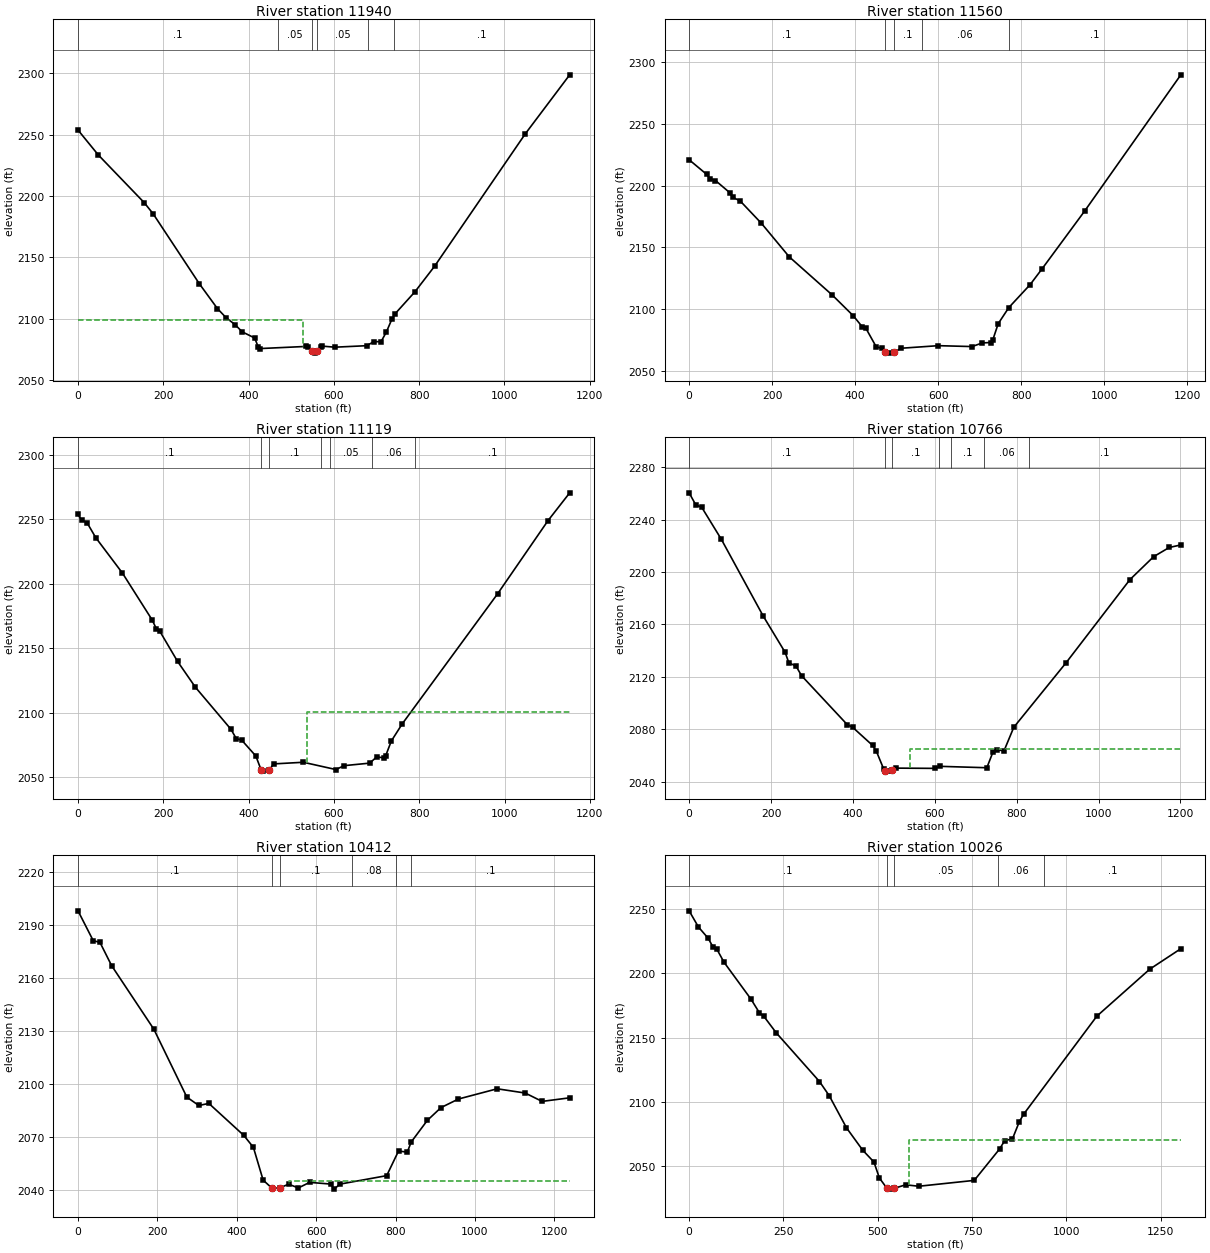
Type RM Length L Ch R = 1 ,11940   ,379.3,379.3,379.3
BEGIN DESCRIPTION:
Structure
END DESCRIPTION:
XS GIS Cut Line= 2
2308989.50991977 721612.524456872309321.27801201722716.738574193
#Sta/Elev= 30
       0 2253.63    47.6 2233.38   155.2 2194.61   176.1 2185.57   284.7 2128.54
     327 2108.42   347.3 2100.99   368.2 2095.42   384.9 2089.55   414.2 2084.51
   422.5 2077.41   426.7 2075.91   535.3 2077.65   539.5 2077.41   547.8 2073.93
   555.1  2072.2   561.5 2074.06   568.7 2077.27   572.9 2077.89   602.1 2077.03
   677.3 2078.25   693.2 2081.48   710.7 2081.55   723.2 2089.46   735.8 2099.64
   744.1 2104.42   790.1 2122.09     836 2142.79    1049 2250.62    1153 2298.54
#Mann= 6 ,-1,0
       0      .1       0     470     .05       0   547.8    .045       0
   561.5     .05       0     680     .06       0     740      .1       0
#XS Ineff= 2 , 0
          526.79 2099.14
Permanent Ineff=
       F       F
Bank Sta=547.8,561.5
XS Rating Curve= 0 ,0
Exp/Cntr(USF)=0,0
Exp/Cntr=0.3,0.1

Type RM Length L Ch R = 1 ,11560   ,441.4,441.4,441.4
XS GIS Cut Line= 2
2308622.73726332721737.6235851552309027.06699044722850.394287132
#Sta/Elev= 30
       0  2220.9    42.1 2209.11    50.6  2205.4    63.4 2204.09    97.4 2194.37
   105.9 2190.35   122.9 2187.55     174 2169.45   241.1 2142.27   344.3 2111.45
   395.3 2094.55   416.6 2085.72   425.1 2084.72   450.6 2069.33   463.4 2068.21
   471.5 2065.28   481.5 2064.29     4942065.058   510.2 2068.24   600.1 2070.33
   681.3  2069.6     706 2072.57   727.3 2072.89   731.5 2075.28   744.3 2088.17
   769.8 2101.19   820.9 2119.68   849.9 2132.58   952.9  2179.6    1184 2289.69
#Mann= 5 ,-1,0
       0      .1       0   471.5    .045       0     494      .1       0
     560     .06       0     770      .1       0
Bank Sta=471.5,494
XS Rating Curve= 0 ,0
Exp/Cntr(USF)=0,0
Exp/Cntr=0.3,0.1

Type RM Length L Ch R = 1 ,11119   ,353,353,353
XS GIS Cut Line= 2
2308256.42144218721893.1350186612308581.26754772722998.994101372
#Sta/Elev= 30
       0 2253.82     8.4 2249.45    20.9 2247.55    41.7 2235.78   104.3 2208.28
   173.8 2172.02   183.4 2165.36   191.8 2163.23   233.5  2139.8   275.2 2119.83
   358.6 2087.22   371.1 2079.93   383.6 2078.87   416.9  2066.5   429.5 2055.53
   433.6 2054.79   447.8 2055.38   458.6 2060.39   528.3 2061.66   604.6 2056.01
   623.6 2059.03   683.8 2060.99   700.4 2065.88   717.1 2065.02   721.3 2066.76
   734.5 2078.17   760.3 2091.56   983.9 2192.42  1101.9 2249.08  1152.6 2270.57
#Mann= 7 ,-1,0
       0      .1       0   429.5    .045       0   447.8      .1       0
     570     .07       0     590     .05       0     690     .06       0
     790      .1       0
#XS Ineff= 2 , 0
                          536.32         2100.43
Permanent Ineff=
       F       F
Bank Sta=429.5,447.8
XS Rating Curve= 0 ,0
Exp/Cntr(USF)=0,0
Exp/Cntr=0.3,0.1

Type RM Length L Ch R = 1 ,10766   ,354,354,354
XS GIS Cut Line= 2
2307841.72428616722010.6325461992308370.46316008723088.845151842
#Sta/Elev= 30
       0 2260.44    16.2 2251.24    30.6 2249.49    78.6 2225.01     181 2166.38
   234.5 2138.73   243.4 2130.85   261.2 2128.17   274.6 2120.91     386 2083.65
   399.3 2081.57   448.3 2067.67   457.3 2063.27   475.1 2049.76     479 2048.45
     485 2048.11   496.1 2048.64   506.3  2050.4   599.8 2050.21   613.2 2051.76
   727.1 2050.69   742.4 2062.94   751.3 2064.38   769.1 2063.63   792.9 2081.55
   920.6 2130.78  1076.5  2194.2  1134.4 2211.71  1172.5 2218.73  1200.9 2220.69
#Mann= 7 ,-1,0
       0      .1       0     479    .045       0   496.1      .1       0
     610     .08       0     640      .1       0     720     .06       0
     830      .1       0
#XS Ineff= 2 , 0
                          538.77         2064.96
Permanent Ineff=
       F       F
Bank Sta=479,496.1
XS Rating Curve= 0 ,0
Exp/Cntr(USF)=0,0
Exp/Cntr=0.3,0.1

Type RM Length L Ch R = 1 ,10412   ,386.2,386.2,386.2
XS GIS Cut Line= 2
2307478.86427465722169.599789339  2308135.468105723220.165917914
#Sta/Elev= 30
       0 2197.85    38.4 2180.95    55.3    2180    84.8 2166.79   191.2 2130.82
   274.2 2092.43   304.4 2087.68   329.7 2088.85   417.6 2070.78   441.9    2064
   466.5 2045.41   488.82040.884   508.42041.054   530.8 2043.15   555.1    2041
   583.6 2044.16   636.3 2043.22   645.7 2040.34   659.6 2043.16   777.8 2047.97
   807.6 2061.91   829.7 2061.28   839.5 2066.99   880.2 2079.25   914.6 2086.49
   958.6 2091.34  1056.1 2097.13  1126.9 2094.72  1169.3 2089.99  1238.9 2092.02
#Mann= 6 ,-1,0
       0      .1       0   488.8    .045       0   508.4      .1       0
     690     .08       0     800     .06       0     840      .1       0
#XS Ineff= 2 , 0
                          530.62          2045.2
Permanent Ineff=
       F       F
Bank Sta=488.8,508.4
XS Rating Curve= 0 ,0
Exp/Cntr(USF)=0,0
Exp/Cntr=0.3,0.1

Type RM Length L Ch R = 1 ,10026   ,368.1,368.1,368.1
XS GIS Cut Line= 2
 2307143.6507402722359.6693191792307855.54752469723451.705163356
#Sta/Elev= 30
       0 2248.56    24.6 2236.01    50.6 2227.17    63.9 2220.07    73.4 2218.77
    92.5 2208.56   164.1  2179.8   186.5 2169.16   197.6 2166.67     231 2153.63
   345.6 2115.76   371.5  2104.7   417.2 2079.74   460.2 2062.35     490 2053.12
   504.4  2040.7   524.7 2032.59   536.6 2032.05  542.872032.554   573.8 2035.42
   608.9 2034.29   755.9 2038.85   823.1 2063.28   836.8 2069.85   857.1 2071.07
   875.6 2084.64   887.2 2090.47  1080.9  2166.6  1221.3 2203.18  1303.6  2219.1
#Mann= 5 ,-1,0
       0      .1       0   524.7    .045       0  542.87     .05       0
     820     .06       0     940      .1       0
#XS Ineff= 2 , 0
                          583.25         2070.26
Permanent Ineff=
       F       F
Bank Sta=524.7,542.87
XS Rating Curve= 0 ,0
Exp/Cntr(USF)=0,0
Exp/Cntr=0.3,0.1

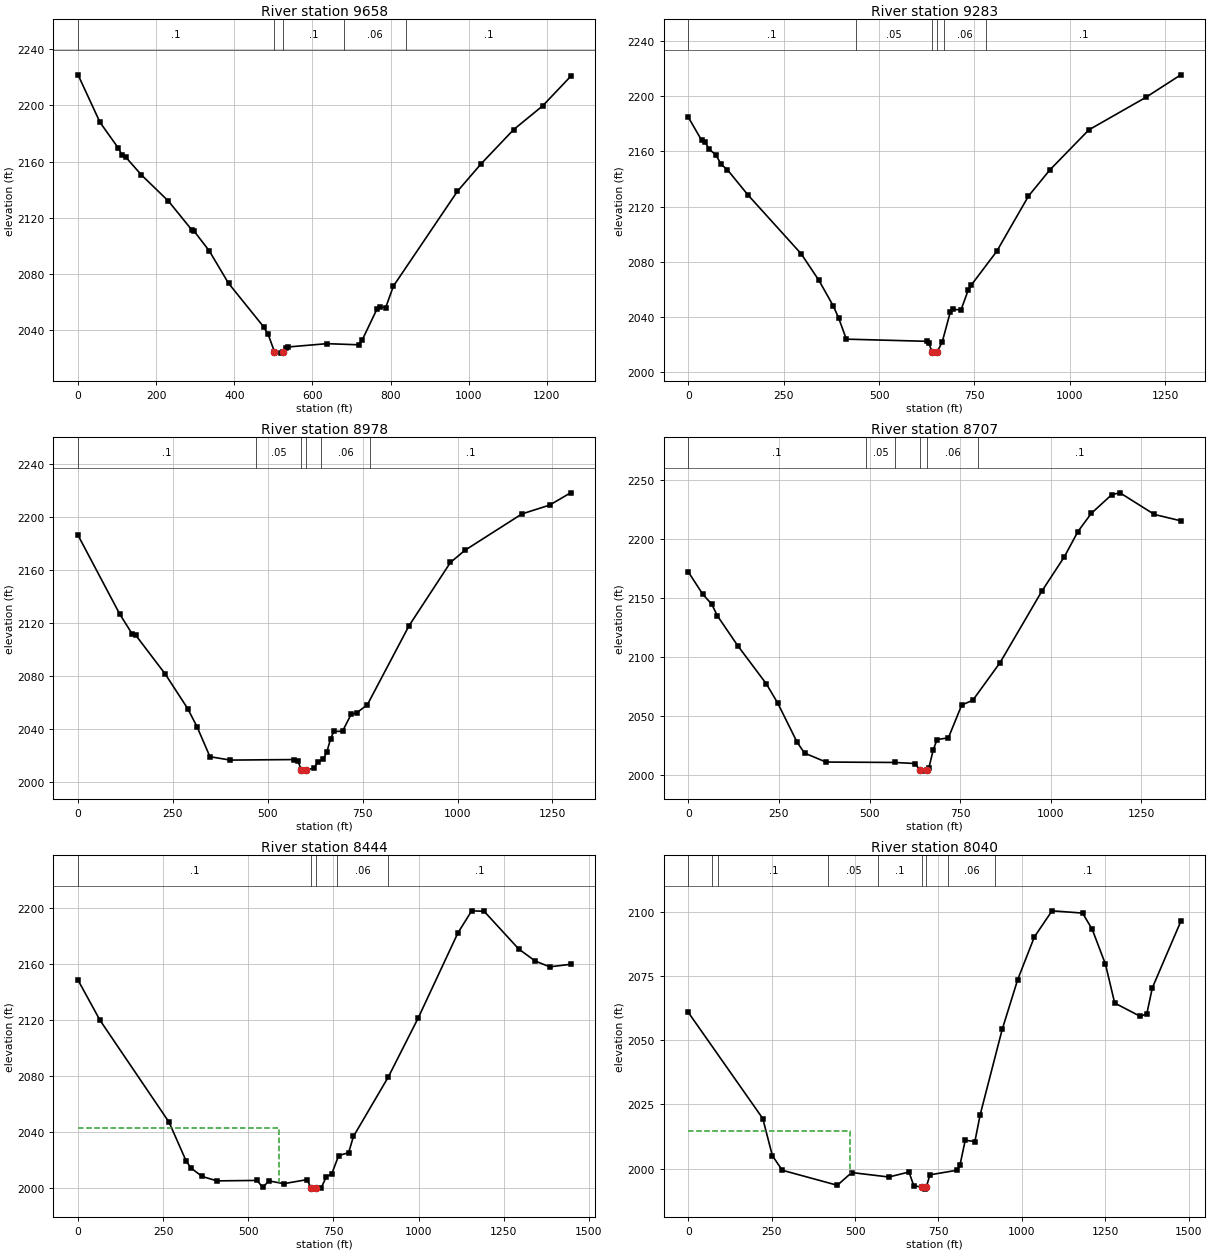
Type RM Length L Ch R = 1 ,9658    ,375,375,375
XS GIS Cut Line= 2
2306836.08368282722594.6643742552307582.53856365723610.672406496
#Sta/Elev= 30
       0  2221.8    56.2    2188   102.4 2169.94   112.3 2164.96   122.2 2163.23
   162.1 2150.61   231.4 2131.97     291 2111.55   297.4 2110.48   335.7 2096.65
   385.2 2073.52   474.7 2042.66   486.6 2037.18   502.6 2024.94   520.4 2023.84
   525.5 2024.48   531.2 2027.28   536.9  2028.2   637.1 2030.57   717.9 2029.77
   727.8 2033.46   765.8 2055.56   772.5  2056.7   787.4 2056.23   807.2 2071.52
     971 2138.94  1031.9 2158.58  1114.9 2182.83  1189.4 2199.77  1260.7 2220.65
#Mann= 5 ,-1,0
       0      .1       0   502.6    .045       0   525.5      .1       0
     680     .06       0     840      .1       0
Bank Sta=502.6,525.5
XS Rating Curve= 0 ,0
Exp/Cntr(USF)=0,0
Exp/Cntr=0.3,0.1

Type RM Length L Ch R = 1 ,9283    ,304.8,304.8,304.8
XS GIS Cut Line= 2
2306642.55834335722770.9106655622307302.61798334723880.225557907
#Sta/Elev= 30
       0 2184.95    34.9 2168.21    43.7 2166.83    55.4 2161.49    72.5 2157.49
    86.4 2150.55   102.1 2146.89   156.2  2128.5   295.9 2085.65   342.4 2066.34
   379.7 2047.94   393.9 2039.19   414.3 2023.61   626.3 2022.03   630.2 2020.76
     639 2014.47   644.8 2013.45   652.4 2014.54   665.3 2021.26   686.9 2043.41
   694.4 2045.25   714.9 2044.87   733.4 2059.06   741.1 2062.68   808.3 2087.37
   891.7 2127.59   947.5 2146.54  1049.9  2175.7  1198.9 2199.26  1290.8 2215.69
#Mann= 6 ,-1,0
       0      .1       0     440     .05       0     639    .045       0
   652.4     .05       0     670     .06       0     780      .1       0
Bank Sta=639,652.4
XS Rating Curve= 0 ,0
Exp/Cntr(USF)=0,0
Exp/Cntr=0.3,0.1

Type RM Length L Ch R = 1 ,8978    ,271.1,271.1,271.1
XS GIS Cut Line= 2
2306377.15472335723009.0701329912307124.54267278 724069.96913237
#Sta/Elev= 30
       0 2186.35   109.4    2127     142    2112   151.8 2110.87   230.1 2081.25
   288.8 2055.32   313.3 2041.65   347.5 2018.89   401.1 2016.32   567.8 2016.72
   579.2 2015.52   588.7 2008.75   592.2 2007.97  600.842008.694   622.3 2010.44
   631.3 2014.71     646 2016.78   655.8 2022.73   665.6 2032.65     674 2037.96
   696.9 2038.18   719.4 2050.91   734.1 2052.06   762.3  2058.2     872 2117.92
   981.1  2165.8  1019.3 2175.01  1169.5 2202.53  1242.4 2209.19  1297.7 2218.48
#Mann= 6 ,-1,0
       0      .1       0     470     .05       0   588.7    .045       0
  600.84     .05       0     640     .06       0     770      .1       0
Bank Sta=588.7,600.84
XS Rating Curve= 0 ,0
Exp/Cntr(USF)=0,0
Exp/Cntr=0.3,0.1

Type RM Length L Ch R = 1 ,8707    ,262.2,262.2,262.2
XS GIS Cut Line= 2
2306127.69880759723209.8296472782307013.04936886724240.376872052
#Sta/Elev= 30
       0 2171.94    39.6 2153.16    65.1 2144.37    80.5 2134.61   136.3 2109.47
   215.4 2077.04   246.7  2060.8   300.5 2027.48   320.8 2018.34     380 2010.78
     570 2010.42   626.8  2009.5   638.1    2004   645.2 2003.08  658.662004.029
   663.7 2005.79   675.9 2021.16   686.3 2029.86   717.5 2031.25   754.4 2059.11
   784.9 2063.12   860.1    2095   975.6 2155.67  1037.5 2184.72  1074.9 2206.09
  1111.8 2221.48  1168.5  2237.4  1190.9 2238.87  1285.9 2220.53  1358.6 2215.17
#Mann= 6 ,-1,0
       0      .1       0     490     .05       0     570      .1       0
   638.1    .045       0  658.66     .06       0     800      .1       0
Bank Sta=638.1,658.66
XS Rating Curve= 0 ,0
Exp/Cntr(USF)=0,0
Exp/Cntr=0.3,0.1

Type RM Length L Ch R = 1 ,8444    ,403.9,403.9,403.9
XS GIS Cut Line= 2
2305836.42312318723446.0958725622306947.18843066724372.233457729
#Sta/Elev= 30
       0 2148.19    64.5 2119.57   267.2 2046.86   317.4 2019.15   331.5  2014.2
   364.2 2008.12   408.1 2004.98   525.7  2005.3     542 2000.36   560.7 2004.97
   603.8 2002.97   673.2  2005.9   683.6  1999.7   687.1 1999.09   697.5 1999.78
   713.2 1999.63   729.4  2008.1   744.4 2009.69   765.3 2023.04   794.4 2025.07
   808.6 2036.67   911.1 2079.15   998.9 2121.26  1115.3 2181.87  1155.8 2197.66
  1192.3 2197.33  1294.2 2170.35  1342.5 2161.81  1385.1  2157.7  1446.2  2159.5
#Mann= 5 ,-1,0
       0      .1       0   683.6    .045       0   697.5      .1       0
     760     .06       0     910      .1       0
#XS Ineff= 2 , 0
          590.32 2042.67
Permanent Ineff=
       F       F
Bank Sta=683.6,697.5
XS Rating Curve= 0 ,0
Exp/Cntr(USF)=0,0
Exp/Cntr=0.3,0.1

Type RM Length L Ch R = 1 ,8040    ,236.4,236.4,236.4
XS GIS Cut Line= 2
2305586.69450321723796.0765050842306812.74664497724619.043011198
#Sta/Elev= 30
       0 2060.92   223.4 2019.51   252.3 2004.98   281.9 1999.33     447 1993.47
     490 1998.43   601.4  1996.7   661.8 1998.64   676.2 1993.28   700.3 1992.77
     710 1991.97   713.9 1992.83   724.4 1997.54   806.3 1999.35   814.8 2001.47
   830.4 2011.02   859.3 2010.54   875.3 2021.03   941.2 2054.26   987.7 2073.67
  1037.6  2090.3  1090.6 2100.49  1182.1 2099.61    1211 2093.29  1250.8 2079.67
  1278.4 2064.54  1355.5 2059.31  1374.8 2060.38  1391.3 2070.47  1476.6 2096.36
#Mann= 9 ,-1,0
       0      .1       0      70     .05       0      90      .1       0
     420     .05       0     570      .1       0   700.3    .045       0
   713.9      .1       0     780     .06       0     920      .1       0
#XS Ineff= 2 , 0
          484.04 2014.52
Permanent Ineff=
       F       F
Bank Sta=700.3,713.9
XS Rating Curve= 0 ,0
Exp/Cntr(USF)=0,0
Exp/Cntr=0.3,0.1

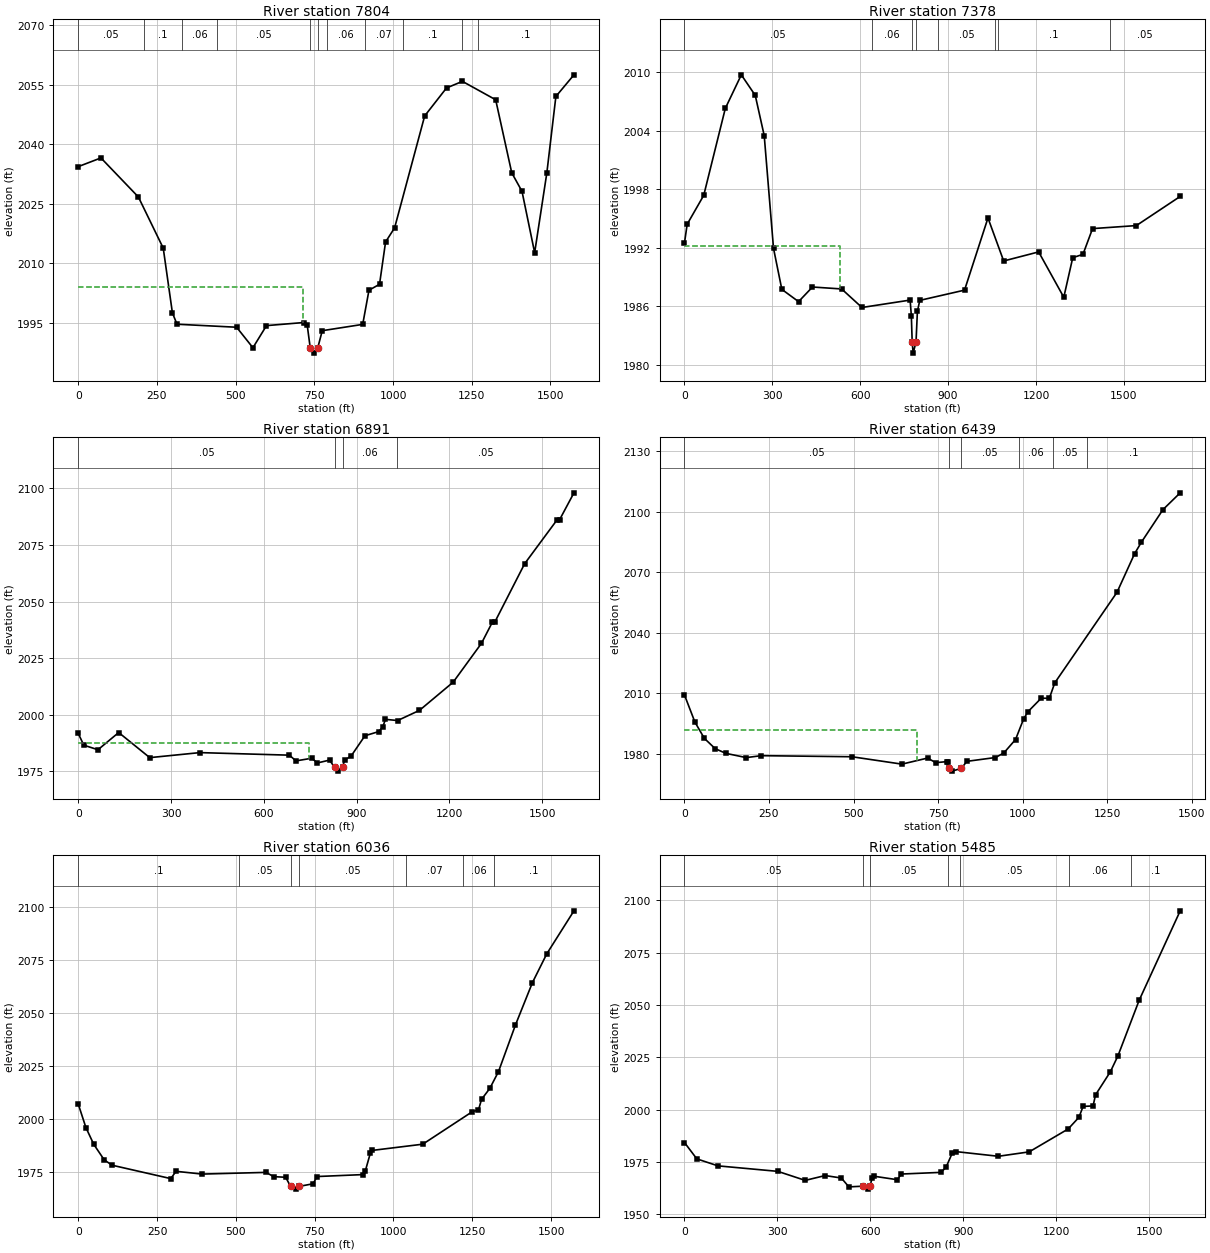
Type RM Length L Ch R = 1 ,7804    ,426,426,426
XS GIS Cut Line= 2
2305392.51051007723948.7918075372306708.13723754724813.746400698
#Sta/Elev= 30
       0 2034.32    72.2 2036.52   191.1 2026.67   270.1 2013.76   299.2 1997.43
   313.8 1994.57   503.1 1993.81   554.9 1988.64     598 1994.22   716.3    1995
   727.2 1994.42   736.8 1988.68   748.1 1987.28   761.11988.688   775.1 1992.94
   903.6 1994.53   923.5 2003.15     957 2004.64   976.2 2015.32  1004.9 2018.88
  1100.4 2047.11  1169.8 2054.17  1220.3 2055.83  1325.9 2051.19  1376.9 2032.77
  1409.5 2028.09  1449.7 2012.61  1488.4 2032.74  1517.1 2052.02  1574.5 2057.48
#Mann= 11 ,-1,0
       0     .05       0     210      .1       0     330     .06       0
     440     .05       0   736.8    .045       0   761.1     .05       0
     790     .06       0     910     .07       0    1030      .1       0
    1220     .06       0    1270      .1       0
#XS Ineff= 2 , 0
          713.93 2003.86
Permanent Ineff=
       F       F
Bank Sta=736.8,761.1
XS Rating Curve= 0 ,0
Exp/Cntr(USF)=0,0
Exp/Cntr=0.3,0.1

Type RM Length L Ch R = 1 ,7378    ,486.6,486.6,486.6
BEGIN DESCRIPTION:
Structure
END DESCRIPTION:
XS GIS Cut Line= 6
2305181.10560615724203.4440285792305758.38501625724698.055073739
2305853.13404633724713.5455851092305941.41113457724706.776781892
2306047.19692879724711.735490996 2306596.4890864725042.286230405
#Sta/Elev= 30
       0 1992.49     9.3 1994.42    65.8 1997.38   139.5  2006.3   194.1 2009.74
   241.7 2007.63   272.3  2003.5     304 1991.95   332.4 1987.74   389.5 1986.48
     437 1987.98   536.6 1987.78   605.9 1985.88   770.4 1986.64   774.5 1985.03
   777.4 1982.33   780.7  1981.2   790.5 1982.34   795.2  1985.5   803.4 1986.61
   956.1 1987.66  1036.1 1995.06  1089.7 1990.65  1209.1 1991.58  1294.9 1986.93
  1325.5 1990.99  1360.4 1991.33  1393.1 1993.97  1542.6 1994.28  1692.3 1997.27
#Mann= 8 ,-1,0
       0     .05       0     640     .06       0   777.4    .045       0
   790.5     .06       0  866.75     .05       0 1061.19     .06       0
 1071.19      .1       0 1451.19     .05       0
#XS Ineff= 2 , 0
          531.15 1992.15
Permanent Ineff=
       F       F
Bank Sta=777.4,790.5
XS Rating Curve= 0 ,0
Exp/Cntr(USF)=0,0
Exp/Cntr=0.3,0.1

Type RM Length L Ch R = 1 ,6891    ,452.6,452.6,452.6
XS GIS Cut Line= 3
2305112.58992976724279.0980923042305582.85650469 725300.80821044
2305393.78067184725739.526274389
#Sta/Elev= 30
       0 1991.76    18.1 1986.54    63.9 1984.53   130.9 1992.13   231.3 1981.04
   393.3 1983.26   682.7 1982.13   703.9  1979.6   755.3 1980.78   772.9 1978.68
   812.5 1979.96  828.791976.729   838.9 1975.08   854.81976.747   860.9 1979.97
   881.8 1981.67     927 1990.72     971 1992.52   984.3 1994.57   993.3 1997.95
  1032.5 1997.43  1103.1 2001.92  1212.2 2014.39  1303.6 2031.55  1338.6 2040.83
  1347.3 2041.09  1443.1  2066.7  1547.6 2086.02  1556.4 2086.22  1602.5 2098.02
#Mann= 4 ,-1,0
       0     .05       0  828.79    .045       0   854.8     .06       0
    1030     .05       0
#XS Ineff= 2 , 0
          746.36 1987.33
Permanent Ineff=
       F       F
Bank Sta=828.79,854.8
XS Rating Curve= 0 ,0
Exp/Cntr(USF)=0,0
Exp/Cntr=0.3,0.1

Type RM Length L Ch R = 1 ,6439    ,402.5,402.5,402.5
XS GIS Cut Line= 2
2305006.22010924724318.2869735482305042.10171998725784.059534886
#Sta/Elev= 30
       0 2009.18    30.9  1995.7    58.9 1987.62    90.9  1982.5   122.9 1980.17
   182.9 1978.08     227 1979.04     495 1978.51   643.1 1974.84   719.1 1977.85
   743.1 1975.57   775.1 1976.07   779.1 1975.66   783.1 1972.85   791.1 1971.37
   819.1 1972.72   835.1 1976.22   919.7 1978.12   944.3 1980.34   979.2 1987.05
  1003.2 1997.31  1016.3 2000.91  1055.2 2007.56  1079.2 2007.49  1095.2 2015.15
  1279.3 2060.09  1331.3 2079.24  1351.3 2084.91  1415.3 2101.12  1466.2 2109.43
#Mann= 6 ,-1,0
       0     .05       0   783.1    .045       0   819.1     .05       0
     990     .06       0    1090     .05       0    1190      .1       0
#XS Ineff= 2 , 0
          687.36 1991.72
Permanent Ineff=
       F       F
Bank Sta=783.1,819.1
XS Rating Curve= 0 ,0
Exp/Cntr(USF)=0,0
Exp/Cntr=0.3,0.1

Type RM Length L Ch R = 1 ,6036    ,551,551,551
XS GIS Cut Line= 2
2304843.86617266 724329.483796762304436.45228718725848.441268358
#Sta/Elev= 30
       0 2007.05    24.5 1995.85    49.4 1987.94    82.5 1980.62   107.4 1978.09
   293.7 1971.76   310.3 1975.21   393.1  1973.9     596  1974.7   619.9  1972.7
   658.2 1972.38   673.5 1968.12   691.3 1966.79   699.6 1968.05   745.1 1969.32
   757.6 1972.74   902.5 1973.65   910.6 1975.28   926.9 1983.88   931.5 1985.06
    1093 1988.02  1250.7 2003.43  1269.8 2004.22  1279.4 2009.19  1305.7 2014.38
  1333.2  2022.3    1387 2044.33  1440.9 2064.37  1486.4 2077.96  1572.6 2098.28
#Mann= 7 ,-1,0
       0      .1       0     510     .05       0   673.5    .045       0
   699.6     .05       0    1040     .07       0    1220     .06       0
    1320      .1       0
Bank Sta=673.5,699.6
XS Rating Curve= 0 ,0
Exp/Cntr(USF)=0,0
Exp/Cntr=0.3,0.1

Type RM Length L Ch R = 1 ,5485    ,679.2,679.2,679.2
XS GIS Cut Line= 2
2304272.82818883724273.4996806982304109.45812283725864.982470824
#Sta/Elev= 30
       0 1984.23    39.9 1976.41   108.2 1973.07   301.3 1970.44   389.7 1966.13
   454.1 1968.44   506.3 1967.26   530.5 1963.03   574.7 1963.34   590.8 1961.95
  598.681963.296   605.7 1967.35   610.9 1968.13   687.3 1966.44   699.3 1969.16
   827.9 1969.96   844.1 1972.39   863.7    1979   876.3 1979.88    1013 1977.65
  1112.5 1979.76  1238.2  1990.7    1273 1996.27  1286.4 2001.48  1318.6 2001.73
  1326.6 2007.01  1374.6 2018.09    1399  2025.7  1467.3  2052.2  1599.8 2094.97
#Mann= 7 ,-1,0
       0     .05       0   574.7    .045       0  598.68     .05       0
     850     .06       0     890     .05       0    1240     .06       0
    1440      .1       0
Bank Sta=574.7,598.68
XS Rating Curve= 0 ,0
Exp/Cntr(USF)=0,0
Exp/Cntr=0.3,0.1