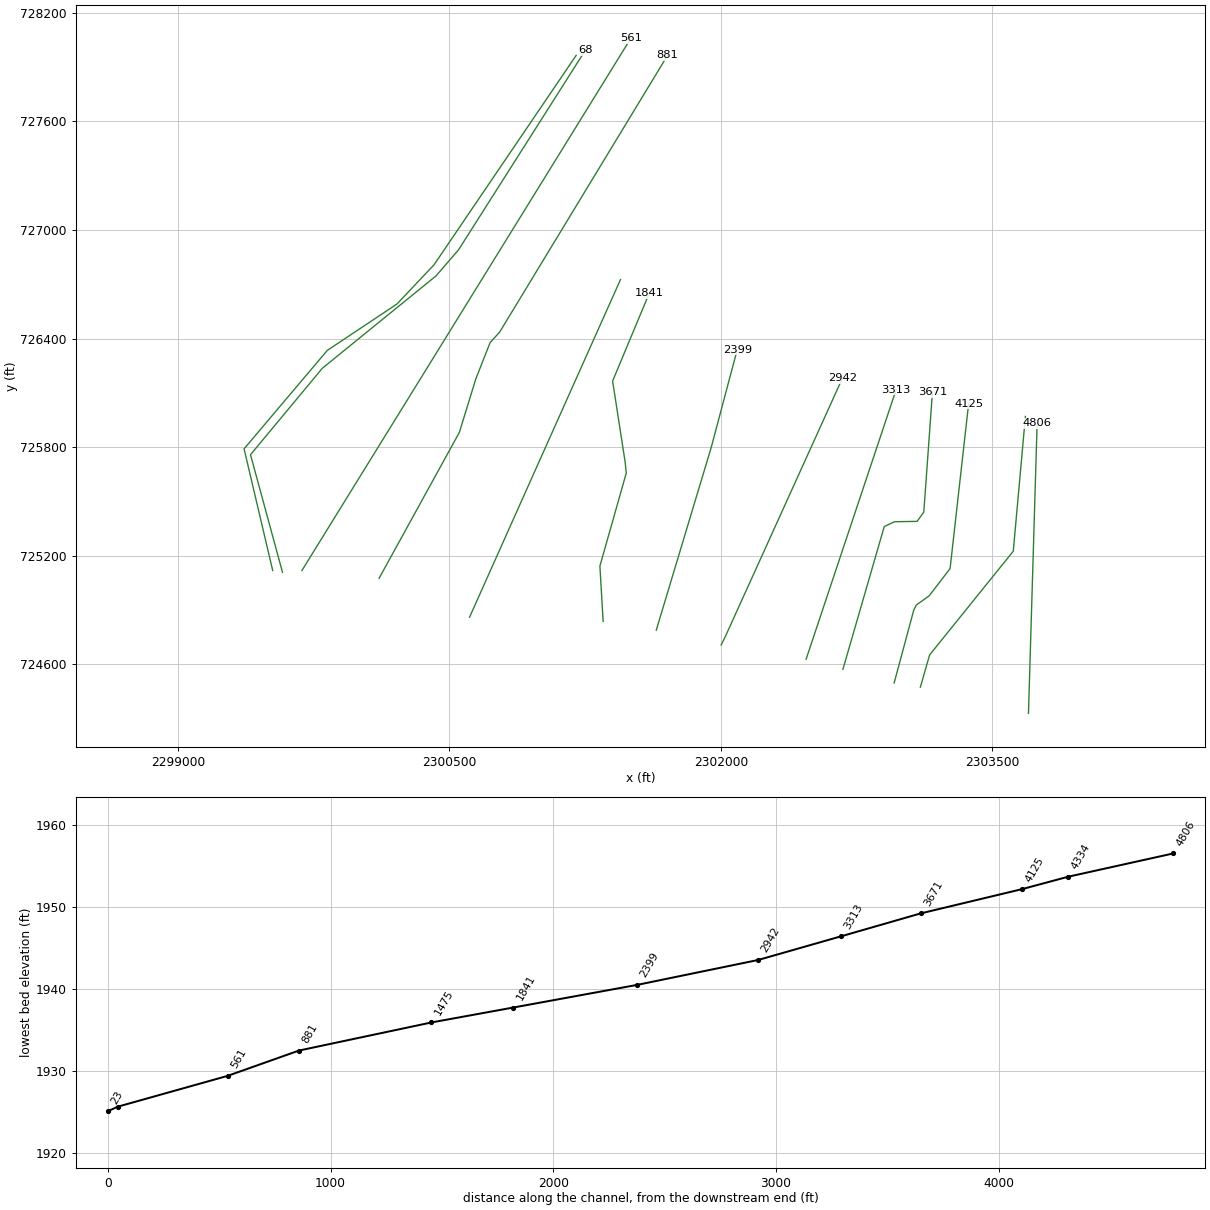
HEC-RAS study STALNAKRN2.prj: STALNAKRN2

--- STALNAKRN2.g01 (geometry) --- (continued)

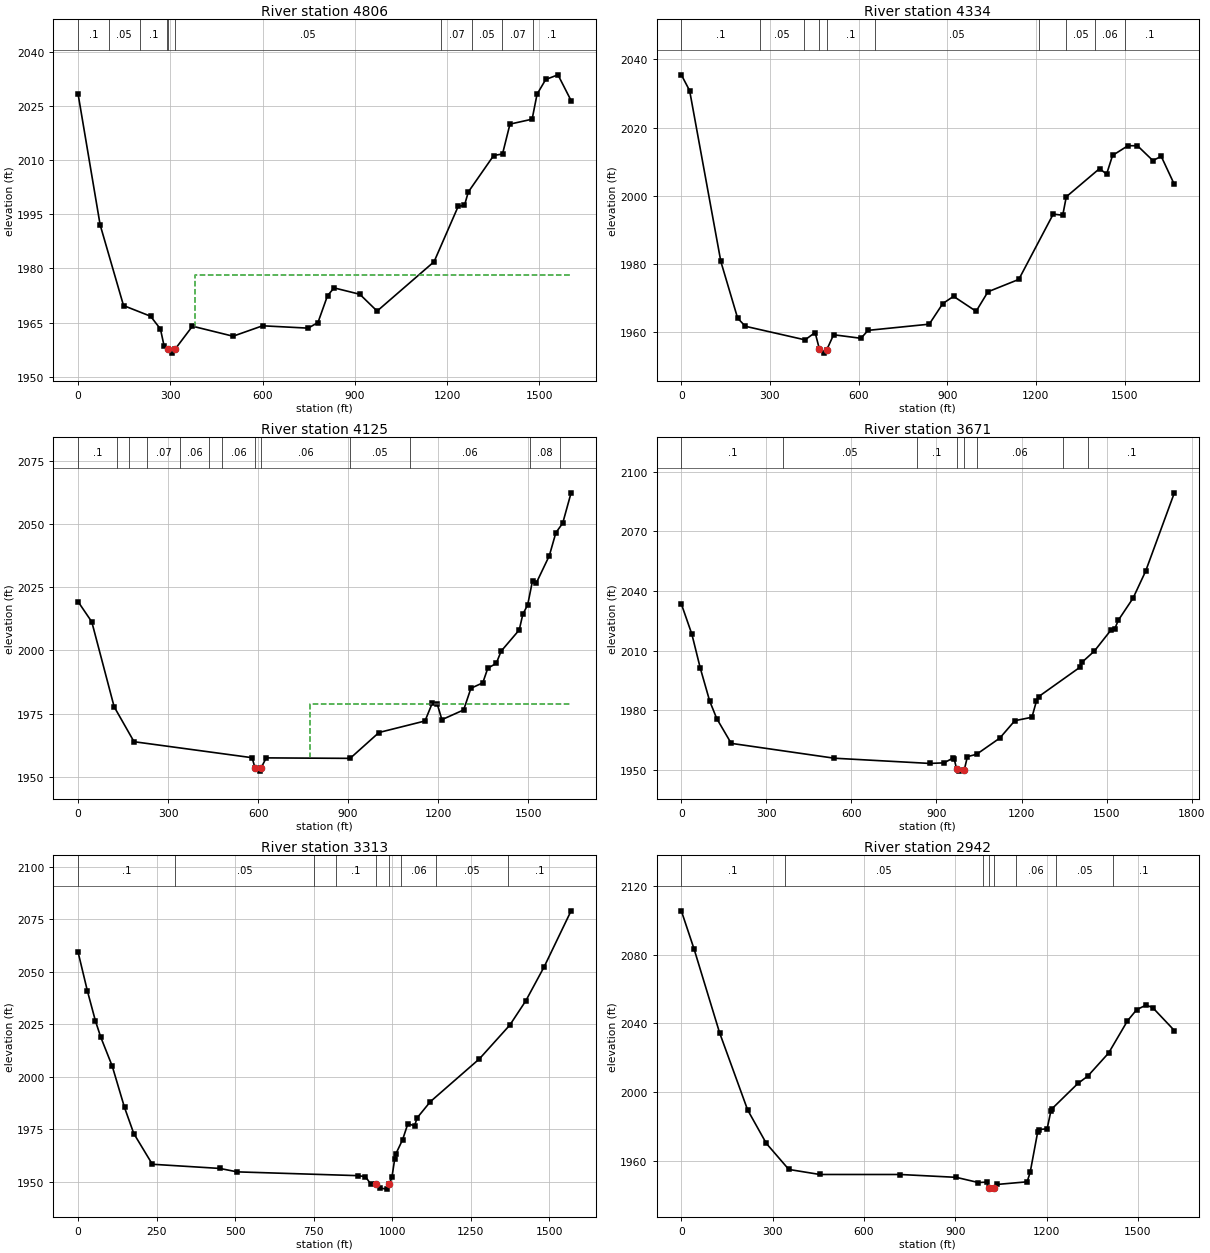
Type RM Length L Ch R = 1 ,4806    ,472.6,472.6,472.6
XS GIS Cut Line= 2
2303698.99099919 724329.48379676 2303746.8315302725931.909377745
#Sta/Elev= 30
       0  2028.4    71.7 1992.12   147.8 1969.72   235.8 1966.76   267.8 1963.22
   279.8  1958.5   291.8 1957.64   303.8 1956.53   315.8 1957.66   371.9    1964
   503.9 1961.22     600 1964.11     748 1963.46     780 1965.01   811.1 1972.46
   832.4 1974.62   916.1 1972.85   972.3 1968.19  1157.6 1981.88  1236.2 1997.27
  1256.3 1997.48  1268.9 2001.22  1351.4 2011.33  1380.1 2011.75  1404.3 2020.03
  1476.4  2021.4  1492.4 2028.33  1520.6 2032.41  1560.4  2033.7  1603.1 2026.55
#Mann= 10 ,-1,0
       0      .1       0     100     .05       0     200      .1       0
     290     .05       0   291.8    .045       0   315.8     .05       0
    1180     .07       0    1280     .05       0    1380     .07       0
    1480      .1       0
#XS Ineff= 2 , 0
                          380.79          1978.1
Permanent Ineff=
       F       F
Bank Sta=291.8,315.8
XS Rating Curve= 0 ,0
Exp/Cntr(USF)=0,0
Exp/Cntr=0.3,0.1

Type RM Length L Ch R = 1 ,4334    ,208.4,208.4,208.4
XS GIS Cut Line= 4
2303101.81314991724474.1506568772303152.86940281724652.290974623
 2303615.0148251725225.2296537562303682.09027114725969.522531176
#Sta/Elev= 30
       0 2035.49    28.1 2030.84   133.7 1980.63   190.6 1963.96   216.7 1961.58
   418.7 1957.59   452.8 1959.75  467.52 1954.81   484.5 1953.69492.31311954.697
   515.4 1959.09   607.9 1958.05     632 1960.38   839.1  1962.2     885 1968.26
   921.4 1970.38   997.7 1965.98  1037.8 1971.72  1142.2 1975.36  1258.7 1994.55
  1290.9 1994.22  1302.9 1999.64  1415.4 2007.92  1439.4 2006.31  1459.5  2011.8
  1511.7 2014.66  1543.9 2014.64  1596.1 2010.28  1624.2 2011.54  1668.7 2003.26
#Mann= 10 ,-1,0
       0      .1       0  265.31     .05       0  415.31      .1       0
  467.52    .045       0492.3131      .1       0  655.31     .05       0
 1211.41     .06       0 1301.41     .05       0 1401.41     .06       0
 1501.41      .1       0
Bank Sta=467.52,492.3131
XS Rating Curve= 0 ,0
Exp/Cntr(USF)=0,0
Exp/Cntr=0.3,0.1

Type RM Length L Ch R = 1 ,4125    ,454,454,454
BEGIN DESCRIPTION:
Structure
END DESCRIPTION:
XS GIS Cut Line= 6
2302956.89285545724497.0789979642303065.35985423724900.166436949
2303079.59484247724928.1248891912303150.48363563724978.842074547
 2303266.0202861725129.2384220222303368.53861715726040.957436133
#Sta/Elev= 30
       0 2019.34    45.7 2011.34   120.2 1977.69   186.5 1963.83     580 1957.49
   589.9 1953.38   605.6 1952.17     610 1953.46   627.1 1957.42   906.7 1957.23
  1002.9 1967.48  1156.3 1972.05  1180.5 1979.13  1196.6 1978.95  1212.6 1972.57
  1285.1 1976.43  1309.3 1985.01  1348.8 1987.16  1365.6 1992.97  1393.8 1994.88
  1409.9  1999.7  1470.3 2008.12  1482.4 2014.38  1498.4 2018.03  1514.6 2027.62
  1526.7 2026.61  1570.7 2037.58  1592.4 2046.66  1615.2 2050.44  1643.2 2062.48
#Mann= 13 ,-1,0
       0      .1       0     130     .05       0     170     .06       0
     230     .07       0     340     .06       0  437.43     .05       0
   478.8     .06       0   589.9    .045       0     610     .06       0
   906.8     .05       0  1106.8     .06       0  1506.8     .08       0
  1606.8      .1       0
#XS Ineff= 2 , 0
                          773.29         1978.86
Permanent Ineff=
       F       F
Bank Sta=589.9,610
XS Rating Curve= 0 ,0
Exp/Cntr(USF)=0,0
Exp/Cntr=0.3,0.1

Type RM Length L Ch R = 1 ,3671    ,358.7,358.7,358.7
BEGIN DESCRIPTION:
Structure
END DESCRIPTION:
XS GIS Cut Line= 6
2302674.14250611724573.1658255942302902.42264239725361.539068722
2302959.56003124725388.067142118 2303084.0379141725390.107763148
2303120.76909265 725441.123288912303168.51163374726102.399234806
#Sta/Elev= 30
       0 2033.47    37.2  2018.2    66.6 2001.25     100 1984.53   124.9  1975.7
     176 1963.21   539.4 1955.73     876  1953.1   926.6 1953.39   958.4 1955.82
   962.7 1955.21   971.1  1950.2   979.5 1949.22  998.291950.005    1009 1956.51
  1041.5 1957.71  1123.3 1965.87  1176.3 1974.63  1236.6 1976.37  1252.5 1984.48
  1260.5 1986.78  1404.9 2001.45  1412.9 2004.03  1456.6 2009.68  1516.8 2020.55
  1529.2 2021.04  1541.2 2025.22  1593.4  2036.4  1637.5 2049.91    1739 2089.45
#Mann= 8 ,-1,0
       0      .1       0     360     .05       0  830.76      .1       0
   971.1    .045       0  998.29      .1       0 1043.11     .06       0
 1345.97     .05       0 1435.97      .1       0
Bank Sta=971.1,998.29
XS Rating Curve= 0 ,0
Exp/Cntr(USF)=0,0
Exp/Cntr=0.3,0.1

Type RM Length L Ch R = 1 ,3313    ,370.6,370.6,370.6
XS GIS Cut Line= 2
  2302470.737446724628.8811987862302968.14970904726118.164786168
#Sta/Elev= 30
       0 2059.27    29.8 2040.72    55.1 2026.62      72 2018.88   108.9 2004.94
   147.9 1985.31   177.4  1972.9   236.5 1958.26   451.6 1956.27   506.4 1954.64
   890.1 1952.84   915.4 1952.37   932.3 1948.75   949.2 1948.82   961.8 1946.95
   982.9 1946.42   991.4 1948.67   999.8 1952.23  1008.2 1960.56  1012.4  1963.3
  1033.5 1969.92  1050.4  1977.6  1071.5 1976.53  1079.9 1980.36  1122.1 1988.08
  1278.1 2008.43  1375.1 2024.53  1425.7 2036.02  1484.8 2052.38  1570.2 2078.92
#Mann= 9 ,-1,0
       0      .1       0     310     .05       0     750     .06       0
     820      .1       0   949.2    .045       0   991.4      .1       0
    1030     .06       0    1140     .05       0    1370      .1       0
Bank Sta=949.2,991.4
XS Rating Curve= 0 ,0
Exp/Cntr(USF)=0,0
Exp/Cntr=0.3,0.1

Type RM Length L Ch R = 1 ,2942    ,542.4,542.4,542.4
XS GIS Cut Line= 3
2302001.52822744724707.5299692252302023.57409891724751.737439593
2302671.73097217726181.931142765
#Sta/Elev= 30
       0 2105.46      42 2083.16   125.6 2034.57   217.9 1989.58   279.3 1970.13
   353.1    1955     455 1952.07   719.5 1952.06     903 1950.41   975.7 1947.38
  1002.9 1947.65  1010.2 1944.08  1017.1 1943.55  1025.9    1944  1036.1 1946.26
  1135.9 1947.81  1145.9  1953.3  1170.8 1976.96  1175.1 1978.21  1201.6 1978.67
  1214.4 1989.29  1217.4 1990.27  1302.6 2005.01  1335.3 2009.32  1403.6 2022.72
  1465.6 2041.46  1495.8 2047.94  1526.6 2050.62  1548.5 2049.14  1619.6 2035.83
#Mann= 8 ,-1,0
       0      .1       0   339.4     .05       0   989.4      .1       0
  1010.2    .045       0  1025.9      .1       0  1099.4     .06       0
  1229.4     .05       0  1419.4      .1       0
Bank Sta=1010.2,1025.9
XS Rating Curve= 0 ,0
Exp/Cntr(USF)=0,0
Exp/Cntr=0.3,0.1

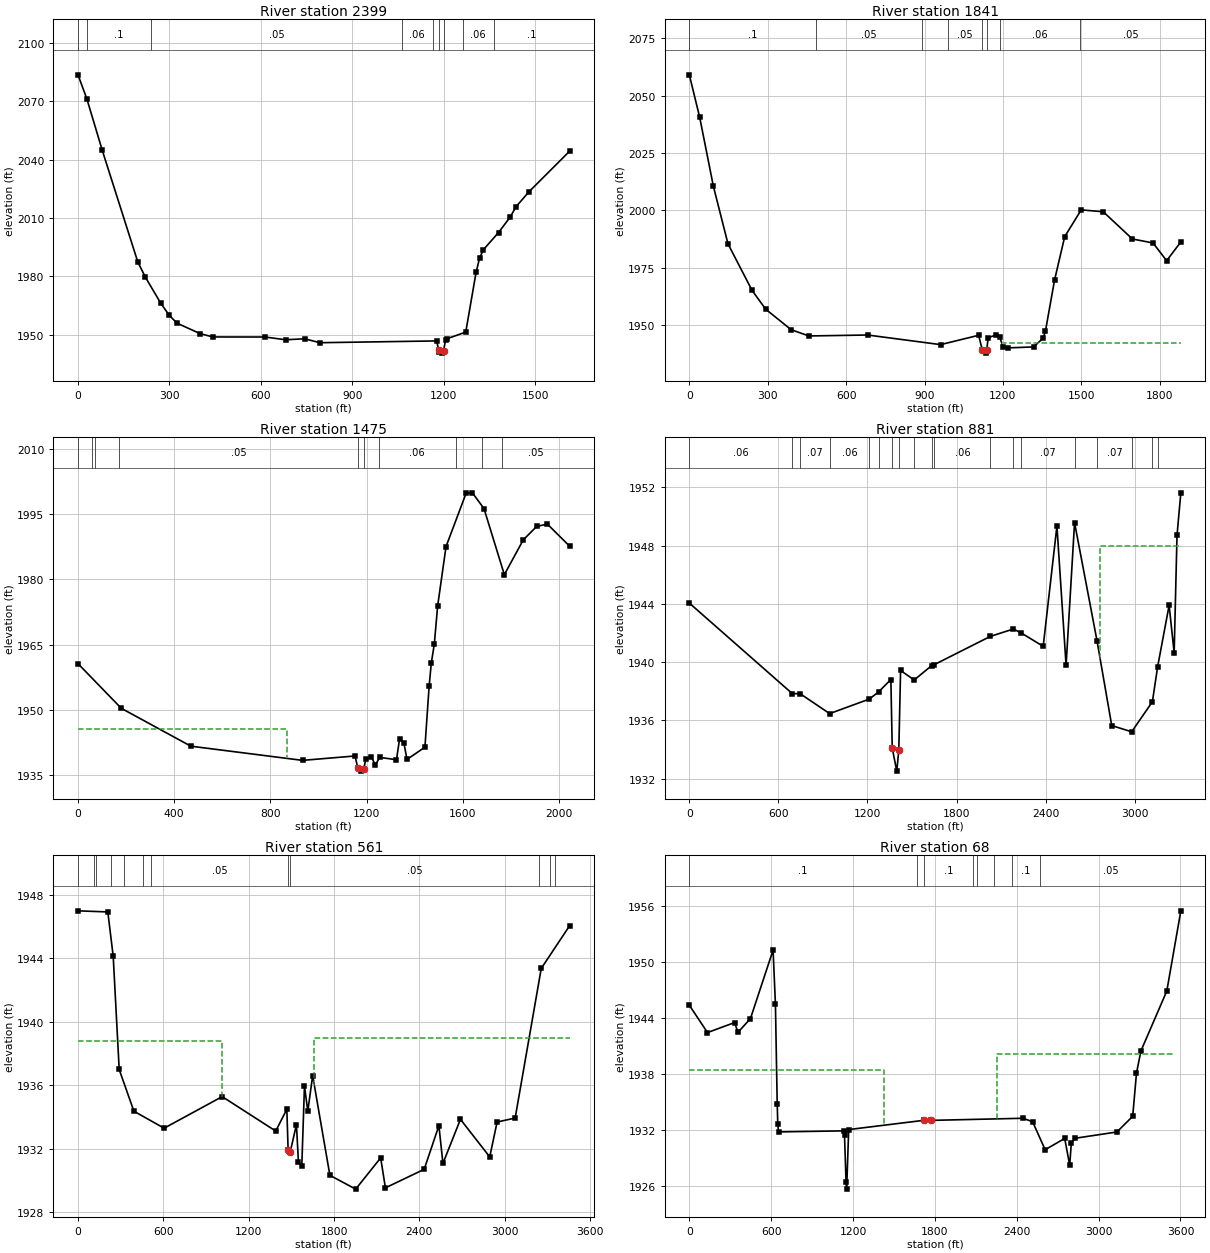
Type RM Length L Ch R = 1 ,2399    ,558.7,558.7,558.7
BEGIN DESCRIPTION:
Structure
END DESCRIPTION:
XS GIS Cut Line= 3
2301643.06632048724789.1853374582301946.36129024725797.657696619
2302090.16385426726338.156988958
#Sta/Elev= 30
       0 2083.65    29.2 2071.21    79.4 2044.94   196.3 1987.35   221.4 1979.49
   271.5  1966.2   299.5 1959.93   325.2  1955.9     401 1950.52   442.8 1948.83
   613.6 1948.81   680.8  1947.4   743.5 1947.89   793.6 1945.88  1176.8  1946.8
  1183.11941.984  1185.1 1940.87  1193.3 1940.52 1199.261941.802  1205.7 1947.18
  1209.9 1947.89    1272 1951.33  1305.9 1982.03  1317.5 1989.49  1329.9 1993.71
  1379.6 2002.54  1417.1 2010.36  1437.5  2015.9  1478.9 2023.42  1612.4 2044.33
#Mann= 9 ,-1,0
       0     .06       0      30      .1       0     240     .05       0
 1063.09     .06       0 1163.09     .07       0  1183.1    .045       0
 1199.26     .07       0 1263.09     .06       0 1363.09      .1       0
Bank Sta=1183.1,1199.26
XS Rating Curve= 0 ,0
Exp/Cntr(USF)=0,0
Exp/Cntr=0.3,0.1

Type RM Length L Ch R = 1 ,1841    ,365.7,365.7,365.7
BEGIN DESCRIPTION:
Structure
END DESCRIPTION:
XS GIS Cut Line= 6
2301349.65838978724837.4836773952301331.65772597725143.015942576
2301477.43718867725657.1674686592301471.31532558725716.345478543
2301401.93421054726165.2821052442301604.83127084726651.313373191
#Sta/Elev= 30
       0 2059.14    39.8 2040.54    91.9  2010.6     148 1985.39   240.1 1965.11
   292.2 1956.92   389.2    1948   457.2 1945.24   682.5 1945.65   961.5 1941.46
  1107.2 1945.53  1120.8 1939.26  1135.6 1937.75 1138.131939.236  1143.7  1944.5
    1172  1945.6  1188.2 1944.63  1200.3 1940.52  1220.6 1940.05  1317.7 1940.45
  1354.2 1944.33  1362.8 1947.36  1397.5 1969.56  1436.5 1988.55  1499.6 2000.23
  1583.9 1999.42  1695.3 1987.55  1774.6 1985.79  1826.6 1978.06  1880.9 1986.27
#Mann= 8 ,-1,0
       0      .1       0  486.06     .05       0  890.48     .06       0
  989.97     .05       0  1120.8    .045       0 1138.13     .05       0
 1189.97     .06       0 1494.24     .05       0
#XS Ineff= 2 , 0
                         1197.11         1942.21
Permanent Ineff=
       F       T
Bank Sta=1120.8,1138.13
XS Rating Curve= 0 ,0
Exp/Cntr(USF)=0,0
Exp/Cntr=0.3,0.1

Type RM Length L Ch R = 1 ,1475    ,594.3,594.3,594.3
XS GIS Cut Line= 2
 2300611.7480096724860.9324485072301445.43534754726725.670231505
#Sta/Elev= 30
       0 1960.63   179.9 1950.37   469.1 1941.67   933.1 1938.41  1151.1 1939.42
  1163.2 1936.65  1175.3 1935.94 1187.471936.527  1196.5 1938.72  1218.3 1939.28
  1235.9 1937.34  1253.4  1939.1  1323.5 1938.56  1336.6  1943.4  1354.2 1942.45
  1367.3 1938.63  1441.8 1941.44  1459.3 1955.52  1468.1 1960.67  1480.9  1965.2
  1494.4 1973.78  1529.4 1987.51  1612.7 1999.75    1639 1999.87  1687.2 1996.25
  1771.8 1981.07  1850.5 1989.07  1906.2 1992.15  1950.5 1992.69  2042.6 1987.64
#Mann= 10 ,-1,0
       0      .1       0      60     .05       0      70      .1       0
     170     .05       0  1163.2    .045       0 1187.47     .05       0
    1250     .06       0    1570     .05       0    1680      .1       0
    1760     .05       0
#XS Ineff= 2 , 0
          867.72 1945.72 1362.39         1939.85
Permanent Ineff=
       F       T
Bank Sta=1163.2,1187.47
XS Rating Curve= 0 ,0
Exp/Cntr(USF)=0,0
Exp/Cntr=0.3,0.1

Type RM Length L Ch R = 1 ,881     ,319.9,319.9,319.9
BEGIN DESCRIPTION:
Structure
END DESCRIPTION:
XS GIS Cut Line= 6
2300111.99184288725075.6272984342300555.46031843725881.830946501
2300646.15458645726176.5873175682300725.51207096726378.382063914
2300777.66127508726435.0659814272301705.16881347727963.641760314
#Sta/Elev= 30
       0 1944.06   693.9 1937.84   745.9 1937.84   945.4 1936.47    1213 1937.47
    1277 1937.98  1357.6 1938.81  1366.8  1934.1  1397.4 1932.52 1410.971933.946
  1423.1 1939.43  1514.8 1938.78    1633 1939.77  1651.5 1939.84  2027.2 1941.77
  2183.2 1942.28  2236.8    1942  2383.7 1941.09  2476.2 1949.35  2537.9 1939.78
    2595 1949.58  2746.6 1941.45  2845.4 1935.65  2979.4 1935.22  3119.1 1937.28
  3154.8  1939.7  3231.9  1943.9  3265.9 1940.65  3285.1 1948.71  3310.9 1951.63
#Mann= 19 ,-1,0
       0     .06       0   693.9     .05       0   745.9     .07       0
   945.4     .06       0    1213     .05       0    1277     .08       0
  1366.8    .045       0 1410.97     .08       0  1514.8     .07       0
    1633     .08       0  1651.5     .06       0  2027.2     .07       0
  2183.2     .05       0  2236.8     .07       0    2595     .05       0
  2746.6     .07       0  2979.4     .05       0  3119.1     .07       0
  3154.8     .05       0
#XS Ineff= 2 , 0
                         2767.15         1947.97
Permanent Ineff=
       F       F
Bank Sta=1366.8,1410.97
XS Rating Curve= 0 ,0
Exp/Cntr(USF)=0,0
Exp/Cntr=0.3,0.1

Type RM Length L Ch R = 1 ,561     ,492.7,492.7,492.7
XS GIS Cut Line= 2
2299685.80846292725118.7533185152301502.41363164728058.230214569
#Sta/Elev= 30
       0 1946.98   209.7 1946.91   247.6 1944.11   289.7 1936.98   393.1 1934.35
   605.6 1933.28  1013.8 1935.27    1390  1933.1  1468.2 1934.47  1477.3 1931.91
 1492.691931.811  1535.8 1933.51  1549.9 1931.12  1573.4 1930.91  1592.2 1935.94
  1615.7 1934.35  1649.7  1936.6  1770.9 1930.31  1952.3 1929.44  2127.9 1931.41
  2161.2 1929.52  2433.9 1930.69  2537.3 1933.44  2565.6 1931.06  2688.8 1933.84
  2894.7 1931.47  2946.4 1933.67  3073.4 1933.92  3256.8 1943.35  3455.5 1946.03
#Mann= 12 ,-1,0
       0     .06       0     110      .1       0     130     .06       0
     230      .1       0     320     .08       0     460      .1       0
     510     .05       0  1477.3    .045       0 1492.69     .05       0
    3240     .06       0    3320     .07       0    3350     .06       0
#XS Ineff= 2 , 0
         1009.04 1938.76 1661.96         1938.95
Permanent Ineff=
       F       F
Bank Sta=1477.3,1492.69
XS Rating Curve= 0 ,0
Exp/Cntr(USF)=0,0
Exp/Cntr=0.3,0.1

Type RM Length L Ch R = 1 ,68      ,45.6,45.6,45.6
BEGIN DESCRIPTION:
Structure
END DESCRIPTION:
XS GIS Cut Line= 6
2299578.44872431725108.6995909262299401.67920519725758.357800576
2299798.16318045726235.538591781 2300426.2209865726745.693849397
 2300551.3220875726890.7812972752301252.41774494727994.033291969
#Sta/Elev= 30
       0 1945.39   133.2 1942.46   331.4 1943.53     357 1942.49   448.2 1943.96
     614  1951.3   631.2 1945.47   644.2 1934.85   648.5 1932.62     654 1931.82
  1131.8 1931.93  1137.5 1931.49  1148.9  1926.4  1153.3 1925.69  1168.2 1932.07
1720.5441933.0631769.0841933.053  2445.9 1933.28  2516.4 1932.91  2608.3 1929.91
  2751.7 1931.12  2788.3 1928.25  2800.3 1930.65  2828.6 1931.14  3134.2 1931.81
  3250.1 1933.49  3277.9 1938.12  3310.3 1940.49  3500.1 1946.91    3603  1955.5
#Mann= 8 ,-1,0
       0      .1       0  1669.2    .045       0 1717.74      .1       0
 2081.79     .05       0 2111.79      .1       0 2231.79     .05       0
 2363.37      .1       0  2572.1     .05       0
#XS Ineff= 2 ,-1
       0 1423.83  1938.4 2258.48  3551.6 1940.21
Permanent Ineff=
       F       F
Bank Sta=1720.544,1769.084
XS Rating Curve= 0 ,0
Exp/Cntr(USF)=0,0
Exp/Cntr=0.3,0.1

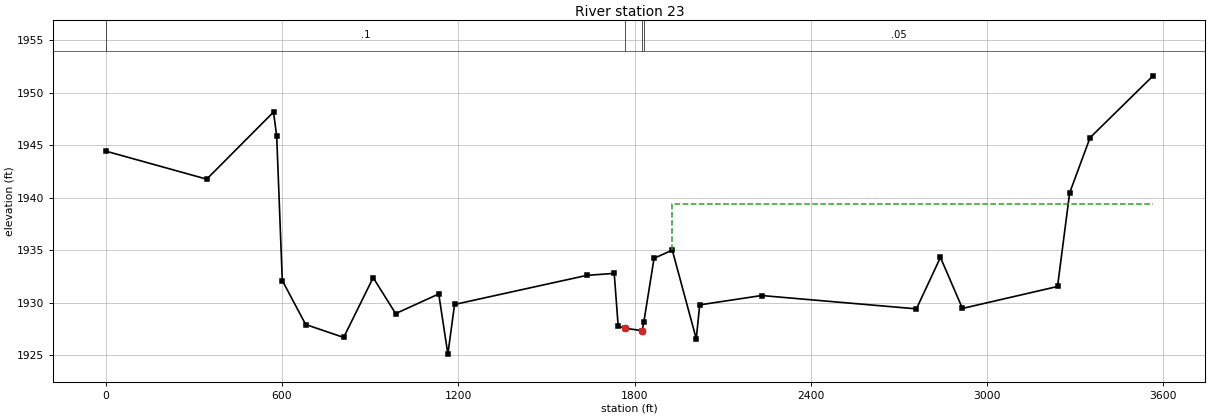
Type RM Length L Ch R = 1 ,23      ,,,
XS GIS Cut Line= 6
2299524.32567069 725118.742128462299366.20539553725790.753297893
2299825.74244522726334.2917437572300210.63951326726590.700987746
2300415.46653132726807.344949152 2301200.6367672727964.092403692
#Sta/Elev= 30
       0 1944.46   343.6 1941.79     571 1948.18   581.9 1945.88   600.9 1932.14
   680.5 1927.95   809.9 1926.72   910.3 1932.41   986.9 1928.99  1133.5 1930.86
  1164.6 1925.13  1187.4 1929.86  1637.7 1932.63  1730.9 1932.82  1744.4  1927.8
  1767.8 1927.59  1825.8 1927.37  1831.8  1928.2  1866.6 1934.26  1928.6 1935.03
  2010.2 1926.58    2022 1929.82  2232.5 1930.71  2759.7 1929.44  2841.5 1934.34
  2916.4 1929.48  3240.1 1931.57  3281.4 1940.49  3350.9 1945.74  3565.3 1951.63
#Mann= 4 ,-1,0
       0      .1       0  1767.8    .045       0  1825.8      .1       0
  1831.8     .05       0
#XS Ineff= 2 , 0
                         1926.51         1939.38
Permanent Ineff=
       F       F
Bank Sta=1767.8,1825.8
XS Rating Curve= 0 ,0
Exp/Cntr(USF)=0,0
Exp/Cntr=0.3,0.1
LCMann Table=0

Chan Stop Cuts=-1
Use User Specified Reach Order=0
Composite Channel Slope=5